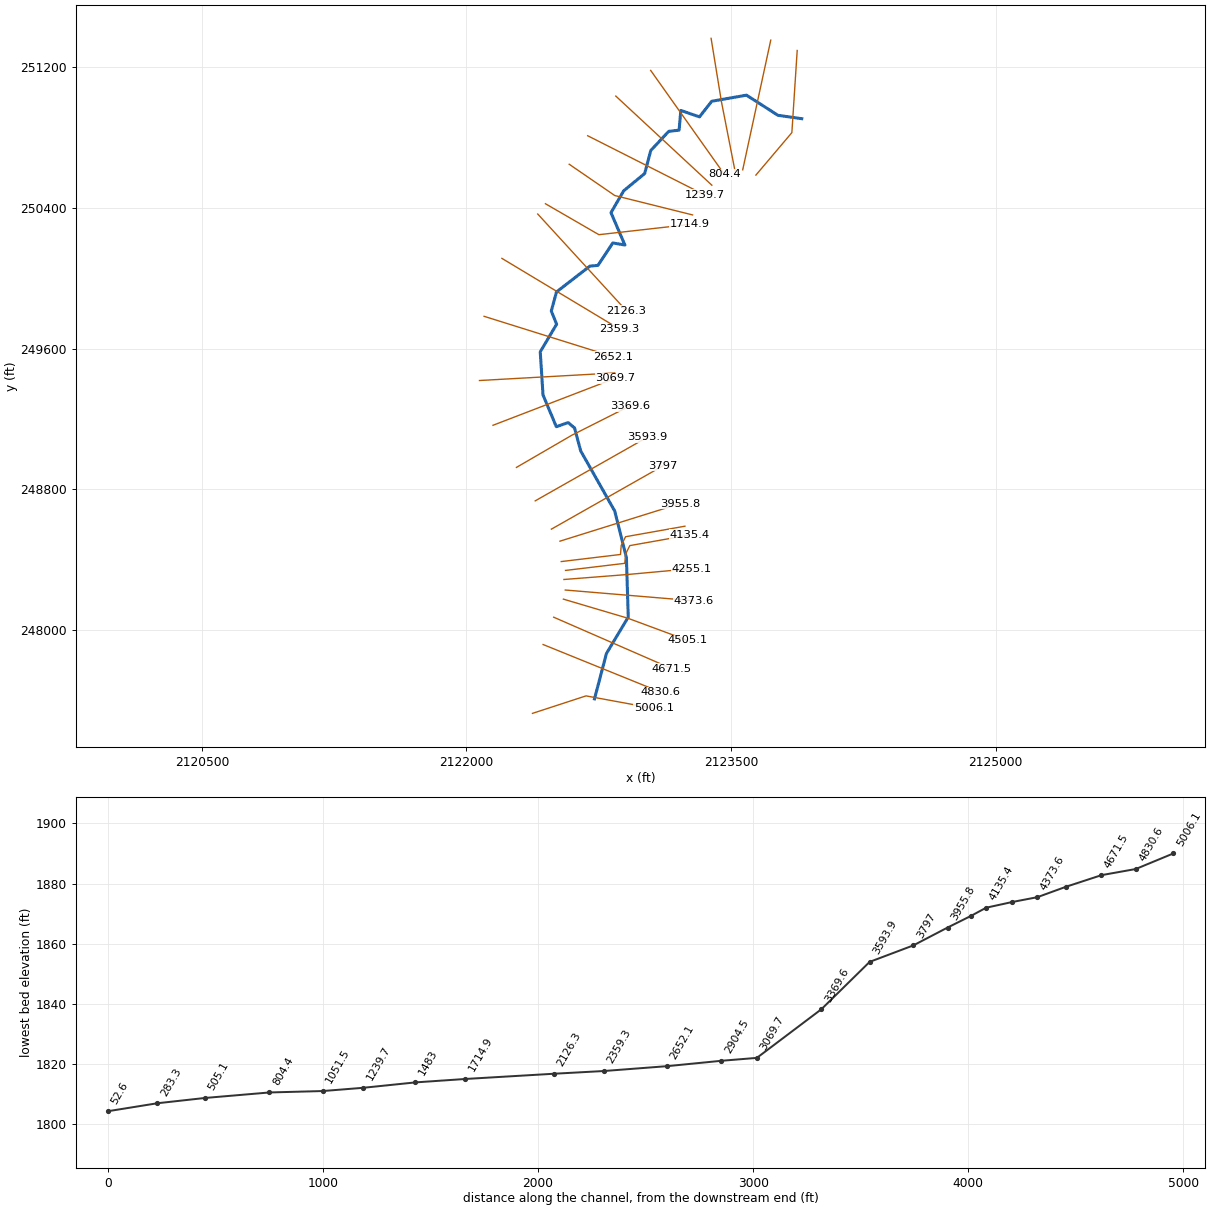
--- SECONDCKT1.prj (project) ---

Proj Title=SECONDCKT1
Current Plan=p01
Default Exp/Contr=0,0
English Units
Geom File=g01
Flow File=f01
Plan File=p01
BEGIN DESCRIPTION:
END DESCRIPTION:
DSS Export Rating Curves= 0
DSS Export Rating Curve Sorted= 0
DSS Export Volume Flow Curves= 0
DXF OffsetX= 0
DXF OffsetY= 0
DXF ScaleX= 0
DXF ScaleY= 0

--- SECONDCKT1.p01 (plan) ---

Plan Title=Floodplain
Program Version=4.00
Geom File=g01
Flow File=f01
K Sum by GR=0
Std Step Tol=0.01
Critical Tol=0.01
Num of Std Step Trials=20
Max Error Tol=0.3
Flow Tol Ratio=0.001
Split Flow NTrial=30
Split Flow Tol=0.02
Split Flow Ratio=0.02
Log Output Level=0
Friction Slope Method=1
Unsteady Friction Slope Method=2
Unsteady Bridges Friction Slope Method=1
Global Log Level=0
CheckData=False
Run HTab=0
Run UNet=0
Run PostProcess=0
UNET Theta=0
UNET Theta Warmup=0
UNET ZTol=0
UNET ZSATol=0
UNET MxIter=0
UNET MaxInSteps=0
UNET DtIC=0
UNET DtMin=0
UNET MaxCRTS=0
UNET WFStab=0
UNET SFStab=0
UNET WFX=0
UNET SFX=0
UNET DSS MLevel=0
UNET DZMax Abort=0
UNET Convert EG Bridges=0
UNET Use Existing IB Tables=0
UNET Froude Limit=0
UNET Froude Power=0
Write IC File=0
Echo Input=False
Echo Output=False
Write Detailed=0

--- SECONDCKT1.f01 (steady flow) ---

Flow Title=NFF Regression Equation
Program Version=4.10
Number of Profiles= 1
Profile Names=P100yr
River Rch & RM=SECONDCKT1,Main            ,5006.1
464.2793
River Rch & RM=SECONDCKT1,Main            ,4671.5
561.1875
River Rch & RM=SECONDCKT1,Main            ,505.1
 620.894
River Rch & RM=SECONDCKT1,Main            ,283.3
623.0194
Boundary for River Rch & Prof#=SECONDCKT1,Main            , 1
Up Type= 0
Dn Type= 3
Dn Slope=0.012
DSS Import GetInterval= 0
DSS Import GetPeak= 0
DSS Import FillOption= 0

--- SECONDCKT1.g01 (geometry) ---

Geom Title=USGS 1m DEM
Program Version=4.10

River Reach=SECONDCKT1      ,Main
Reach XY= 30
     2122725.865      247609.539     2122793.573      247867.351
     2122917.271      248074.383     2122906.854      248412.924
     2122840.448      248677.247      2122647.74      249018.393
     2122612.801      249149.036     2122576.342      249179.417
     2122509.502       249155.98     2122433.981      249336.536
     2122418.356      249581.327     2122511.238      249738.445
     2122480.856      249813.098      2122510.37      249921.605
     2122699.606      250068.306     2122745.613      250072.647
     2122829.815      250200.251     2122898.391      250188.098
     2122819.398      250372.126     2122891.446      250496.258
      2123010.37      250594.348     2123045.092      250725.424
     2123146.655      250833.931     2123205.683      250840.876
     2123215.231      250952.855     2123321.134      250916.397
     2123390.579      251004.938     2123587.627       251039.66
     2123766.447      250925.077     2123900.911      250905.951

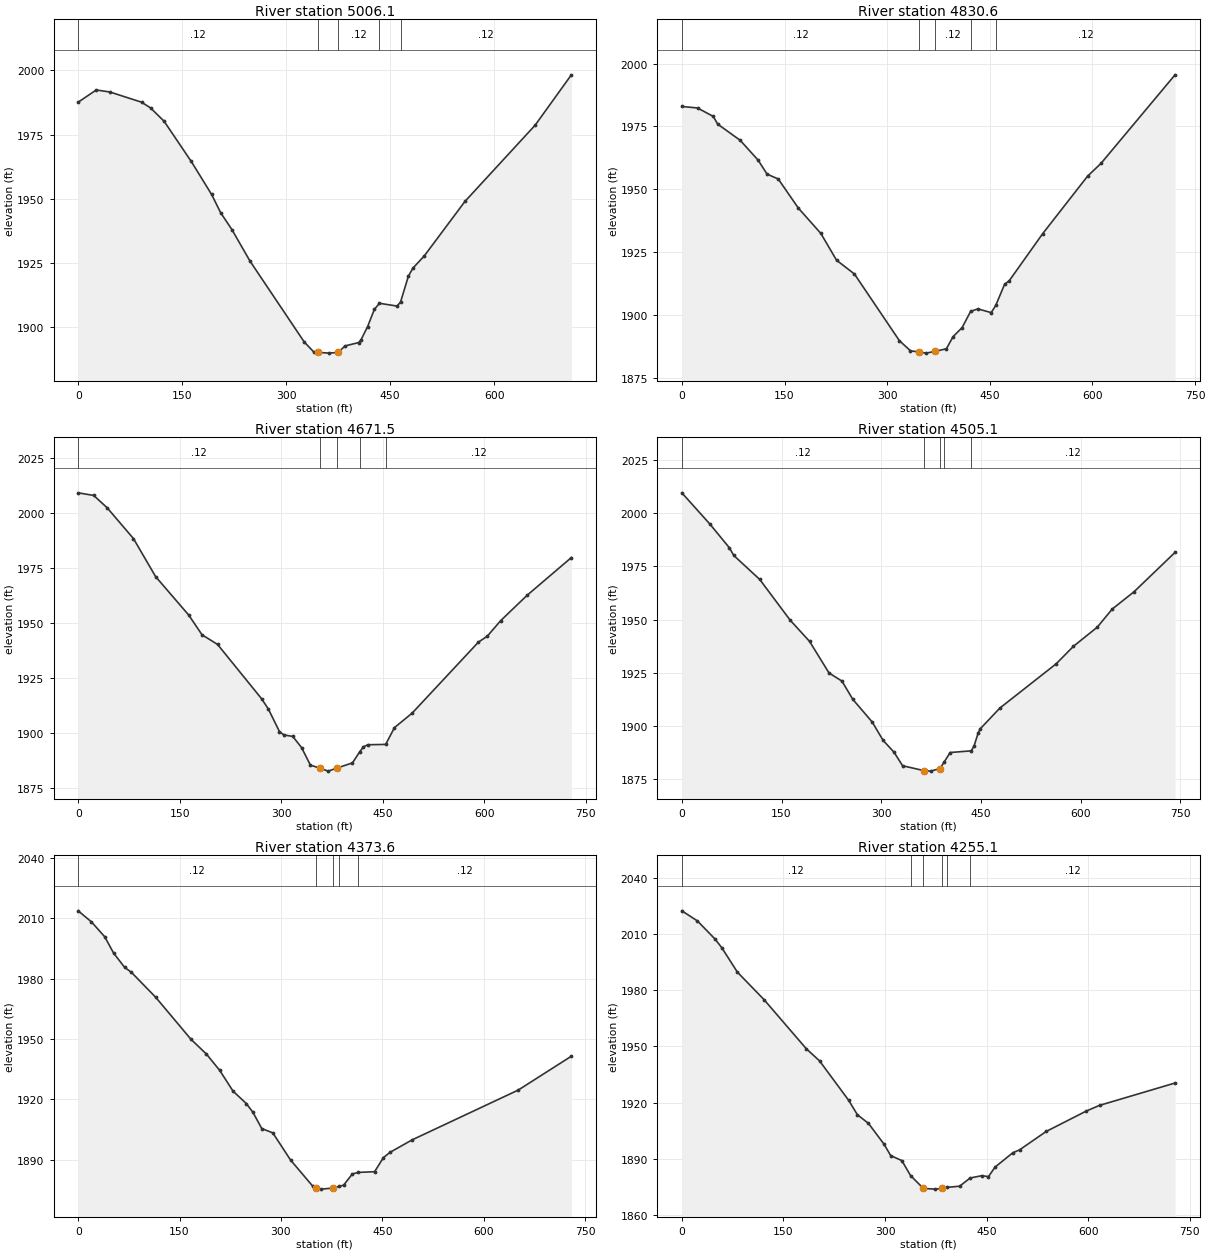
Type RM Length L Ch R = 1 ,5006.1  ,181.9,175.4,168.6
XS GIS Cut Line= 3
     2122374.204      247527.336     2122677.867      247626.704
      2123063.15      247555.632
#Sta/Elev= 30
       0  1987.6    26.1 1992.34    45.6 1991.56    91.3  1987.6   104.3 1985.38
   123.9 1980.18     163 1964.57   192.4 1951.72   205.4 1944.65   221.7 1938.05
   247.8  1925.8     326 1894.36  339.97 1890.41   345.6 1890.31     362 1890.02
     375 1890.31   384.8 1892.81   404.4 1894.13   407.7  1895.1   417.4 1900.34
   427.2 1907.06  434.441909.396   459.9 1908.32  464.891909.874   476.2 1919.93
   482.8 1923.08   499.1 1927.81   557.8 1949.01     659 1978.64   711.3 1998.23
#Mann= 5 ,-1 , 0
       0     .12       0   345.6    .045       0     375     .12       0
  434.44    .016       0  464.89     .12       0
Bank Sta=345.6,375
XS Rating Curve= 0 ,0
Exp/Cntr=0.3,0.1

Type RM Length L Ch R = 1 ,4830.6  ,160.1,159.2,158.2
XS GIS Cut Line= 2
     2122434.727      247918.471     2123102.426      247647.277
#Sta/Elev= 30
       0 1982.96    22.9 1982.35    45.9 1978.99    52.4 1975.92    85.2  1969.5
   111.4 1961.61   124.5 1956.04   140.9 1954.09   170.3  1942.5   203.1 1932.45
     226  1921.8   252.2  1916.3   317.8 1889.81   334.1 1885.74   347.2 1885.24
   357.1 1884.82   369.5  1885.5   386.5 1886.54   396.4  1891.4   409.5 1894.95
   421.91901.388   432.4 1902.43   452.1 1900.94  458.681903.801   471.7 1912.24
   478.3 1913.58   527.4 1932.39   592.9 1955.22   612.6 1960.34   720.7 1995.54
#Mann= 5 ,-1 , 0
       0     .12       0   347.2    .045       0   369.5     .12       0
   421.9    .016       0  458.68     .12       0
Bank Sta=347.2,369.5
XS Rating Curve= 0 ,0
Exp/Cntr=0.3,0.1

Type RM Length L Ch R = 1 ,4671.5  ,161.6,166.3,168.3
XS GIS Cut Line= 2
     2122494.577      248073.707     2123162.276      247781.939
#Sta/Elev= 30
       0 2009.29    22.9  2008.1    42.5 2002.59    81.7 1988.47   114.4  1971.2
   163.4 1953.68     183 1944.75   205.9 1940.38   271.2 1915.59     281 1910.98
   297.4 1900.75   303.9 1899.22     317 1898.57     330  1893.5   343.1 1885.51
   357.5 1884.11   369.2 1882.78   382.3 1884.16   405.2 1886.53  416.271891.693
   421.5 1893.84     428 1894.78  454.261894.919   467.3 1902.56   493.4 1909.14
   591.4 1941.44   604.5 1944.13   624.1 1951.14   663.3 1962.72   728.7 1979.87
#Mann= 5 ,-1 , 0
       0     .12       0   357.5    .045       0   382.3     .12       0
  416.27    .016       0  454.26     .12       0
Bank Sta=357.5,382.3
XS Rating Curve= 0 ,0
Exp/Cntr=0.3,0.1

Type RM Length L Ch R = 1 ,4505.1  ,124,131.6,141.7
XS GIS Cut Line= 3
      2122549.69      248176.349     2122914.886      248067.961
     2123253.306      247942.262
#Sta/Elev= 30
       0 2009.52    42.3 1994.81    71.6 1983.68    78.1 1980.12   117.2 1968.85
   162.8  1949.8   192.1  1939.8   221.4 1924.96   240.9 1921.13   257.2 1912.57
   286.5 1901.89   302.8  1893.3   319.1 1887.81   332.1 1881.41   364.7 1879.08
   374.4 1878.88   388.4 1880.09  394.621883.147   403.7 1887.62  435.391888.407
   439.5 1890.56     446 1896.98   449.2 1898.84   478.5  1908.5   563.1 1929.25
   589.1 1937.46   624.9 1946.43   647.6 1954.99   680.2 1963.05     742 1981.56
#Mann= 5 ,-1 , 0
       0     .12       0   364.7    .045       0   388.4     .12       0
  394.62    .016       0  435.39     .12       0
Bank Sta=364.7,388.4
XS Rating Curve= 0 ,0
Exp/Cntr=0.3,0.1

Type RM Length L Ch R = 1 ,4373.6  ,112.3,118.4,125.1
XS GIS Cut Line= 2
      2122560.28       248228.15     2123287.586      248167.222
#Sta/Elev= 30
       0 2013.69    19.6  2008.2    39.3 2000.79    52.4 1992.69    68.7 1985.62
    78.6 1983.19   114.6 1970.78   166.9 1949.87   189.8 1942.53   209.5 1934.39
   229.1 1924.14   248.7 1917.98   258.6 1913.59   271.6 1905.55     288 1903.39
   314.2 1889.92   346.9 1876.99   351.4 1875.99     360 1875.45   376.4 1875.97
  386.531876.818   392.8 1877.44   405.8 1883.02  414.411883.749   438.6 1884.11
   451.7 1891.11   461.5 1893.74   494.2 1899.93   651.3 1924.68   729.8 1941.48
#Mann= 5 ,-1 , 0
       0     .12       0   351.4    .045       0   376.4     .12       0
  386.53    .016       0  414.41     .12       0
Bank Sta=351.4,376.4
XS Rating Curve= 0 ,0
Exp/Cntr=0.3,0.1

Type RM Length L Ch R = 1 ,4255.1  ,63.5,119.8,163.2
XS GIS Cut Line= 3
     2122552.799         248288.     2122915.721      248316.503
     2123278.185      248349.833
#Sta/Elev= 30
       0 2022.31      23 2016.92    49.2 2007.16      59  2002.6      82 1989.59
   121.4 1974.89   183.7 1948.72   203.3 1942.23     246 1921.33   259.1 1913.53
   275.5 1908.89   298.4 1897.82   308.3 1891.69   324.7 1889.06  337.571881.071
   356.5  1874.2   373.9 1873.82   383.7 1874.22  391.371874.758     410 1875.38
  425.521879.752   442.7 1880.99   452.6 1880.51   462.4  1885.6   488.6 1893.23
   498.5 1894.77   537.8 1904.59   596.9 1915.46   616.5  1918.5     728 1930.44
#Mann= 6 ,-1 , 0
       0     .12       0  337.57     .06       0   356.5    .045       0
   383.7     .12       0  391.37    .016       0  425.52     .12       0
Bank Sta=356.5,383.7
XS Rating Curve= 0 ,0
Exp/Cntr=0.3,0.1

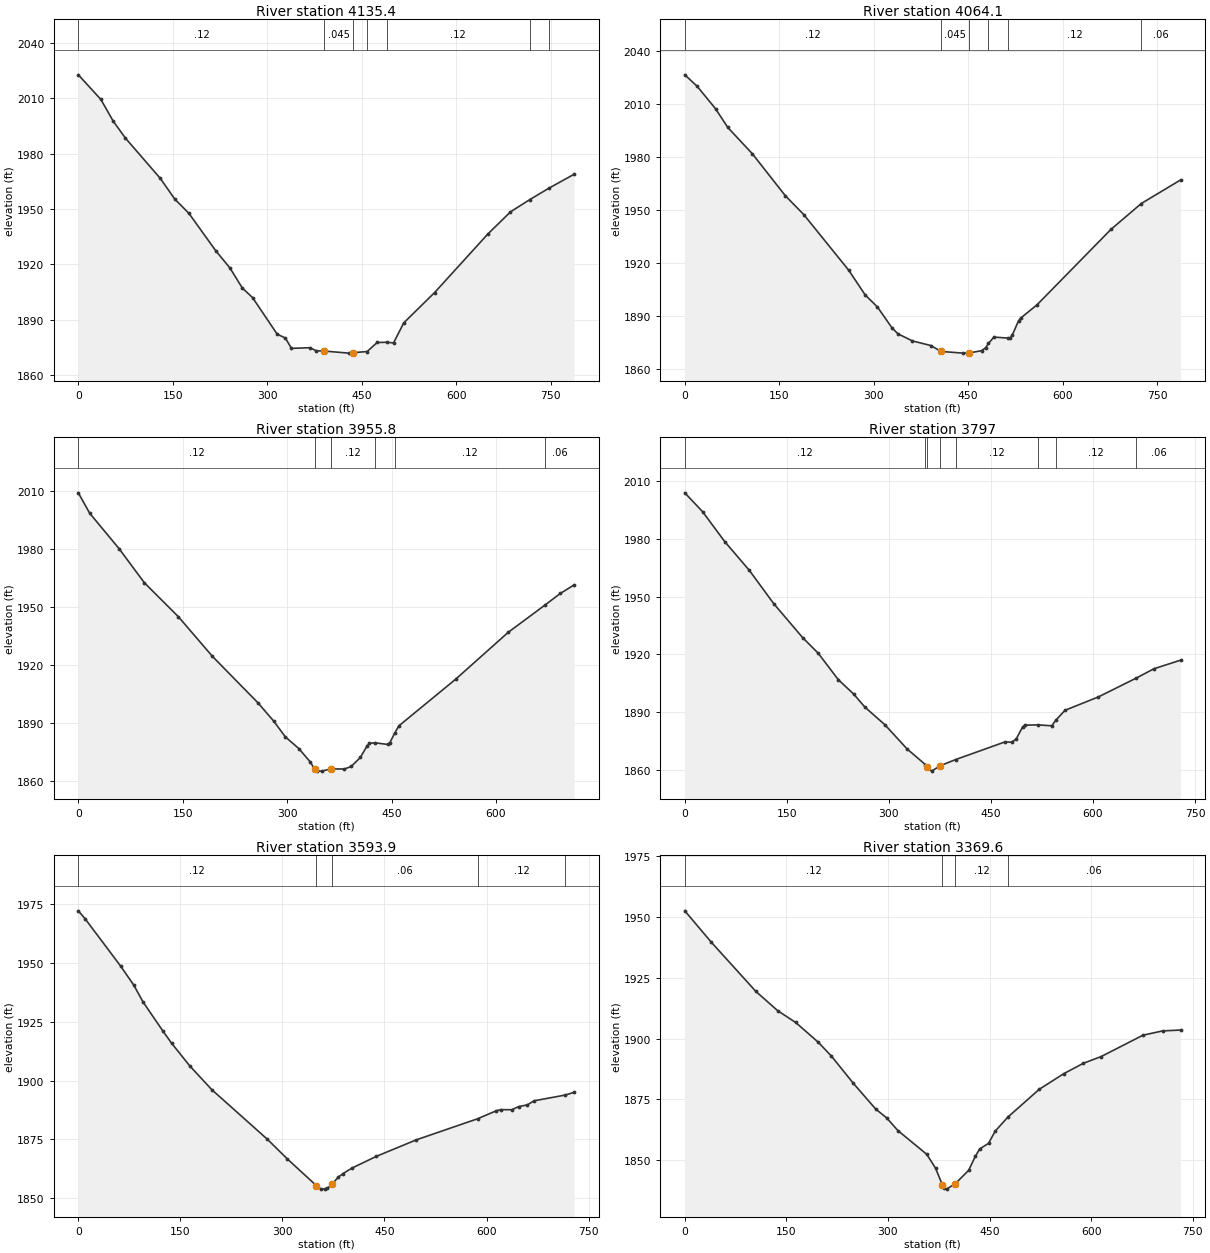
Type RM Length L Ch R = 1 ,4135.4  ,52.9,71.2,54
XS GIS Cut Line= 5
     2122561.575       248339.45       2122897.6      248379.814
      2122901.94      248431.897     2122926.246      248480.509
     2123263.051      248540.404
#Sta/Elev= 30
       0 2022.74    35.8  2009.4    55.3 1997.68    74.8 1988.45   130.2  1966.6
     153 1955.47   175.7 1947.62     218  1927.5   240.8 1918.03   260.3 1907.24
   276.6 1902.04   315.7 1882.22   328.7 1880.11   338.4 1874.53   367.8 1874.88
   377.6 1873.23   390.7 1873.06   429.1 1871.94   435.5 1872.16   458.61872.817
   474.4  1877.7  489.84 1877.82   500.4 1877.47   516.7 1888.35   565.6 1904.75
   650.3 1936.54   686.1 1948.48  716.411955.068  747.971961.485   787.1 1968.87
#Mann= 7 ,-1 , 0
       0     .12       0   390.7    .045       0   435.5     .12       0
   458.6    .016       0  489.84     .12       0  716.41     .06       0
  747.97     .12       0
Bank Sta=390.7,435.5
XS Rating Curve= 0 ,0
Exp/Cntr=0.3,0.1

Type RM Length L Ch R = 1 ,4064.1  ,174.4,108.3,90
XS GIS Cut Line= 5
      2122537.27      248389.797     2122873.294      248430.161
     2122877.635      248482.245      2122901.94      248530.856
     2123238.746      248590.752
#Sta/Elev= 30
       0 2026.74    19.5 2020.31    48.8 2007.55    68.3 1996.94   107.4 1981.99
   159.5 1958.33   188.8 1947.66   260.3  1916.1   286.4 1902.13   305.9  1895.3
   328.7 1883.62   338.4 1880.12   361.3 1876.11   390.7 1873.48   406.7 1870.15
   441.9 1869.19   451.6  1869.3   471.1 1870.57   477.6 1872.22  482.161874.675
   490.7 1878.27  512.33 1877.72   516.7 1877.78     520 1879.47   529.8 1887.42
     533 1888.96   559.1 1896.51   676.4 1939.19  724.711953.873   787.1 1967.24
#Mann= 6 ,-1 , 0
       0     .12       0   406.7    .045       0   451.6     .12       0
  482.16    .016       0  512.33     .12       0  724.71     .06       0
Bank Sta=406.7,451.6
XS Rating Curve= 0 ,0
Exp/Cntr=0.3,0.1

Type RM Length L Ch R = 1 ,3955.8  ,150.7,158.9,166.8
XS GIS Cut Line= 2
     2122530.113      248505.747     2123209.714      248718.602
#Sta/Elev= 30
       0 2009.24    16.3  1998.7    58.8 1980.26    94.7  1962.8   143.7 1945.19
   192.7 1924.65   258.1 1900.64   280.9  1891.1   297.3 1883.09   316.9 1876.96
   333.2 1870.06   339.7 1866.21     343 1865.42   349.5 1865.33   362.6 1866.47
   382.2 1866.43     392 1867.74   405.1 1872.39   414.9 1878.41   418.2 1879.66
  425.871880.005   444.3 1879.13   447.6 1880.08  454.931885.291   460.6 1888.78
   542.3 1912.94   617.4 1937.06  669.941951.093   692.6 1957.26   712.2 1961.62
#Mann= 6 ,-1 , 0
       0     .12       0   339.7    .045       0   362.6     .12       0
  425.87    .016       0  454.93     .12       0  669.94     .06       0
Bank Sta=339.7,362.6
XS Rating Curve= 0 ,0
Exp/Cntr=0.3,0.1

Type RM Length L Ch R = 1 ,3797    ,203.3,203.1,198.1
XS GIS Cut Line= 2
     2122481.572      248574.001     2123115.056      248934.164
#Sta/Elev= 30
       0 2003.92    26.1 1994.15    58.8 1978.56    94.8 1963.69   130.7 1946.39
   173.2 1928.74   196.1 1920.63   225.5 1906.95   248.4 1899.36   264.7 1892.63
   294.1 1883.49   326.8  1870.9  353.641862.783   356.2 1861.72   362.7  1859.4
   375.8 1862.26  397.97 1865.39   470.6 1874.57   480.4 1874.43   486.9 1875.94
   496.7 1882.46     500 1883.27  518.681883.427   539.2 1882.94     5461886.091
   558.8 1890.98   607.8 1897.92  663.571907.717   689.5 1912.55   728.7 1917.02
#Mann= 8 ,-1 , 0
       0     .12       0  353.64     .06       0   356.2    .045       0
   375.8     .06       0  397.97     .12       0  518.68    .016       0
     546     .12       0  663.57     .06       0
Bank Sta=356.2,375.8
XS Rating Curve= 0 ,0
Exp/Cntr=0.3,0.1

Type RM Length L Ch R = 1 ,3593.9  ,225.2,224.3,222.4
XS GIS Cut Line= 2
     2122389.927      248734.848     2123023.411      249095.011
#Sta/Elev= 30
       0 1972.08     9.8 1968.77    62.1 1948.65    81.7 1940.45    94.8 1933.53
   124.2 1921.09   137.2 1915.84   163.4 1906.37   196.1 1896.16   277.8  1875.1
   307.2 1866.73   349.8 1855.43   356.2 1854.01   362.7 1853.91     366 1854.23
   372.5  1855.9   382.3 1859.06   388.9 1860.48   401.9  1862.8   437.9 1867.81
   496.7 1874.83  587.041883.807   614.3 1887.18   620.9 1887.66   637.2 1887.62
     647 1888.94   660.1 1889.69   669.9 1891.42  715.611893.851   728.7 1895.02
#Mann= 5 ,-1 , 0
       0     .12       0   349.8    .045       0   372.5     .06       0
  587.04     .12       0  715.61     .06       0
Bank Sta=349.8,372.5
XS Rating Curve= 0 ,0
Exp/Cntr=0.3,0.1

Type RM Length L Ch R = 1 ,3369.6  ,292.9,299.9,276.2
XS GIS Cut Line= 3
     2122283.352      248924.769     2122597.717      249107.716
     2122926.366      249273.941
#Sta/Elev= 30
       0 1952.57    39.3 1939.62   104.9 1919.45   137.6 1911.41   163.8 1906.66
   196.6 1898.67   216.3  1892.9     249 1881.61   281.8  1871.1   298.2  1867.4
   314.6 1862.24   357.2 1852.48   370.2 1846.78   380.4 1839.87   383.3 1838.57
   386.5 1838.15   399.6 1840.46   419.1 1845.87   428.9 1851.59   435.4 1854.67
   448.5 1856.98   458.2 1861.95  476.89 1867.74   523.4  1879.2   559.3 1885.58
   588.6  1889.9   614.7 1892.65   676.6 1901.45   705.9 1903.22     732 1903.55
#Mann= 4 ,-1 , 0
       0     .12       0   380.4    .045       0   399.6     .12       0
  476.89     .06       0
Bank Sta=380.4,399.6
XS Rating Curve= 0 ,0
Exp/Cntr=0.3,0.1

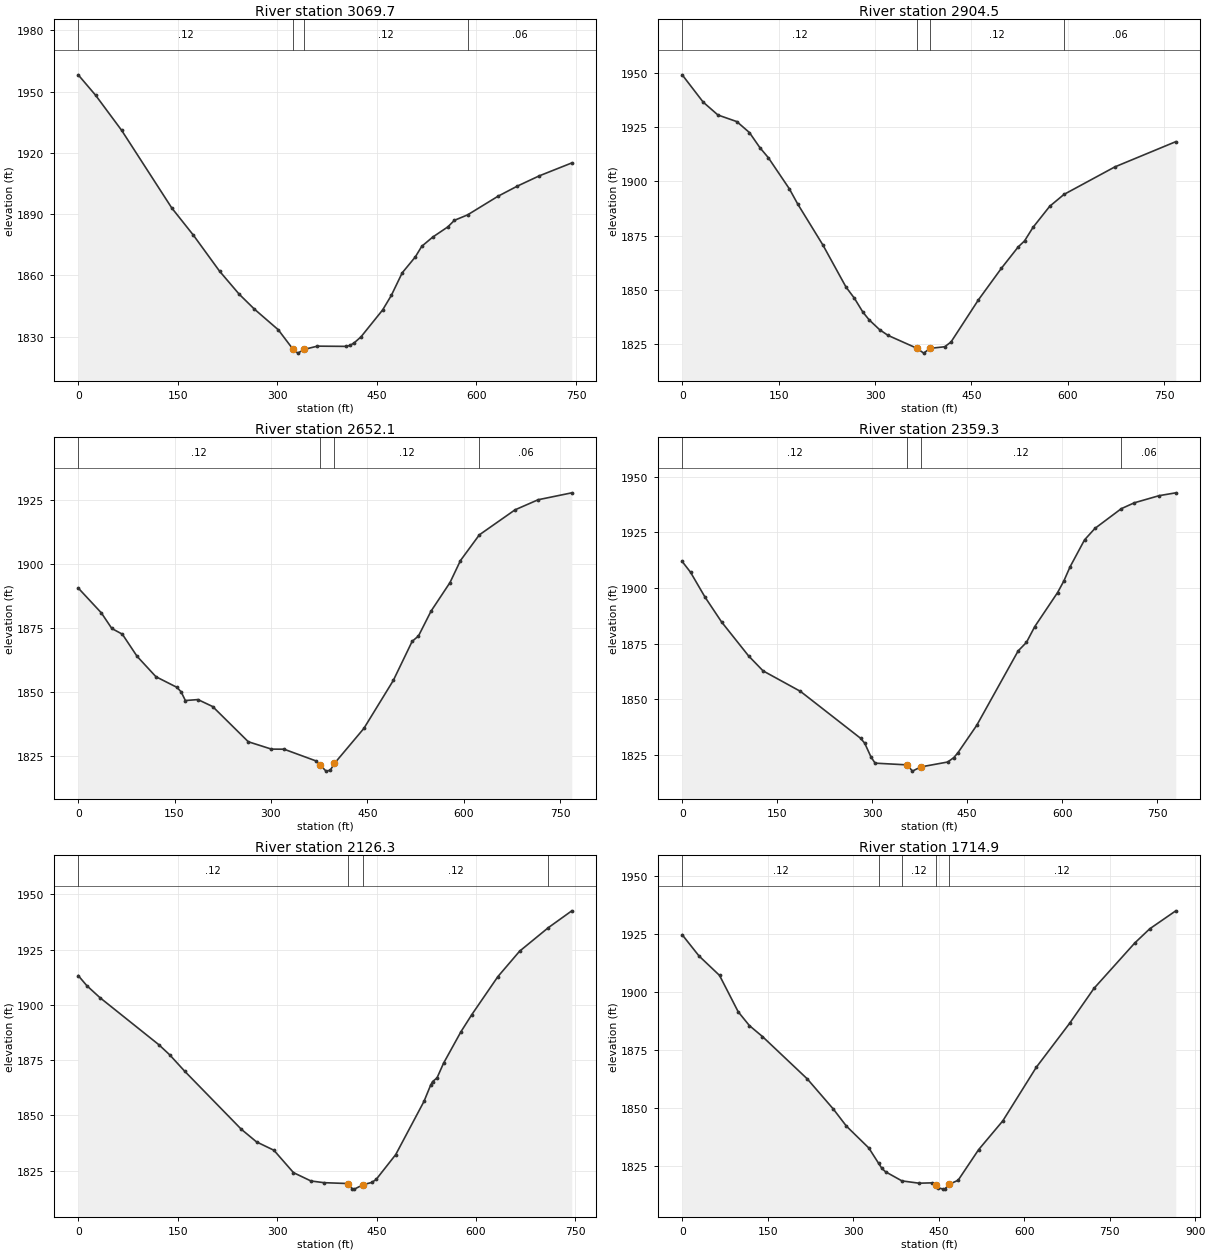
Type RM Length L Ch R = 1 ,3069.7  ,175.6,165.2,152.2
XS GIS Cut Line= 2
     2122150.441      249164.095     2122844.324      249431.549
#Sta/Elev= 30
       0 1958.26    26.2 1948.26    65.5 1931.03   140.9 1893.07   173.6 1879.69
   212.9 1862.12   242.4 1850.86   265.4 1843.52   301.4  1833.4   323.5  1823.9
   330.9 1821.96   340.7 1823.82   360.4 1825.38   402.9 1825.27   409.5 1825.73
     416 1827.07   425.9 1829.89   458.6  1843.1   471.7 1850.22   488.1 1861.28
   507.8 1869.06   517.6 1874.29     534 1878.77   556.9  1883.8   566.7 1886.99
  586.591889.669   632.3 1898.77   661.7 1903.78   694.5 1908.77   743.6 1915.11
#Mann= 4 ,-1 , 0
       0     .12       0   323.5    .045       0   340.7     .12       0
  586.59     .06       0
Bank Sta=323.5,340.7
XS Rating Curve= 0 ,0
Exp/Cntr=0.3,0.1

Type RM Length L Ch R = 1 ,2904.5  ,263.6,252.4,237.3
XS GIS Cut Line= 2
     2122073.758      249418.457     2122840.583      249461.474
#Sta/Elev= 30
       0 1948.94    32.7 1936.37    55.6 1930.47      85 1927.43   104.6  1922.4
   120.9 1915.45     134 1910.85   166.7 1896.54   179.8 1889.51     219 1870.66
   254.9 1851.35     268  1846.2   281.1 1839.86   290.9 1836.28   307.2 1831.76
   320.3 1829.14   364.8 1823.28   375.8 1820.99   385.6 1823.18   408.5 1823.92
   418.3 1826.13   460.8 1845.44   496.8 1860.06   522.9 1869.85   532.7 1872.59
   545.8 1878.79   571.9 1888.52  594.021893.952   673.2 1906.61     768 1918.21
#Mann= 4 ,-1 , 0
       0     .12       0   364.8    .045       0   385.6     .12       0
  594.02     .06       0
Bank Sta=364.8,385.6
XS Rating Curve= 0 ,0
Exp/Cntr=0.3,0.1

Type RM Length L Ch R = 1 ,2652.1  ,307.3,292.8,268.7
XS GIS Cut Line= 2
     2122099.942      249783.166     2122833.102      249553.119
#Sta/Elev= 30
       0 1890.59      36 1880.89    52.3 1874.81    68.7 1872.58    91.6 1863.97
     121    1856   153.7 1851.86   160.2 1850.11   166.8 1846.72   186.4 1847.09
   209.3 1844.38   264.8 1830.65   300.8 1827.78   320.4 1827.75   369.5 1823.24
     376 1821.78   385.8  1819.2   392.4 1819.56   398.9 1822.21   444.7 1835.85
   490.5 1854.54   519.9  1869.8   529.7 1871.88   549.3 1881.58   578.8 1892.72
   595.1  1901.3  624.461911.307   680.1 1921.07   716.1    1925   768.4 1927.69
#Mann= 4 ,-1 , 0
       0     .12       0     376    .045       0   398.9     .12       0
  624.46     .06       0
Bank Sta=376,398.9
XS Rating Curve= 0 ,0
Exp/Cntr=0.3,0.1

Type RM Length L Ch R = 1 ,2359.3  ,242.7,233,224.1
XS GIS Cut Line= 2
     2122200.939       250112.34     2122868.638      249710.224
#Sta/Elev= 30
       0 1911.94    13.1 1907.11      36 1895.92    62.2 1884.72   104.8 1869.45
   127.7 1862.71   186.7 1853.49   281.6 1832.39   288.2 1830.16     298 1824.02
   304.6 1821.18   355.4  1820.4   363.5 1817.59   376.6 1819.47   419.2 1821.69
     429  1823.7   435.6 1825.95     465 1838.16   530.5  1871.7   543.6 1875.54
   556.7 1882.63   592.8 1897.98   602.6 1903.14   612.4  1909.5   635.3 1921.66
   651.7 1926.82  693.331935.701   713.9 1938.35   753.2 1941.57   779.4 1942.84
#Mann= 4 ,-1 , 0
       0     .12       0   355.4    .045       0   376.6     .12       0
  693.33     .06       0
Bank Sta=355.4,376.6
XS Rating Curve= 0 ,0
Exp/Cntr=0.3,0.1

Type RM Length L Ch R = 1 ,2126.3  ,279.1,411.4,401.6
XS GIS Cut Line= 2
     2122404.023      250364.454     2122906.577      249815.103
#Sta/Elev= 30
       0 1913.29    13.1 1908.68    32.8 1903.29   121.4 1882.06   137.8 1877.49
   160.7 1869.99     246 1843.76     269 1838.04   295.2 1834.26   324.7 1824.14
     351 1820.37   370.6  1819.6   406.7 1819.21   413.3 1816.84   416.6 1816.68
   429.7 1818.69   442.8 1819.71   449.4 1821.06   478.9  1832.3   521.5 1856.34
   531.4 1863.58   534.6 1865.35   541.2 1866.98     551  1873.6   577.3 1887.88
   593.7 1895.63     633 1912.81   665.8 1924.32  709.151934.964   744.5 1942.57
#Mann= 4 ,-1 , 0
       0     .12       0   406.7    .045       0   429.7     .12       0
  709.15     .06       0
Bank Sta=406.7,429.7
XS Rating Curve= 0 ,0
Exp/Cntr=0.3,0.1

Type RM Length L Ch R = 1 ,1714.9  ,245,232,221.3
XS GIS Cut Line= 3
     2122447.819      250422.811     2122750.809      250247.002
     2123263.272      250304.981
#Sta/Elev= 30
       0 1924.71    29.5 1915.56    65.5 1907.17    98.2 1891.48   117.9 1885.51
   140.8 1880.79   219.4 1862.52   265.2 1849.48   288.1 1842.13   327.4  1832.7
  344.531826.104   350.3 1823.89   356.8 1822.42  385.51 1818.49   415.6  1817.5
   438.4 1817.65     445  1816.7   448.2 1815.58     458 1814.94   461.3 1815.06
   467.8 1816.96   484.1 1818.76     520 1831.95   562.5  1844.4   621.2  1867.5
     680 1886.59   722.4 1901.55   794.2  1921.2   820.3 1927.28     866 1935.04
#Mann= 5 ,-1 , 0
       0     .12       0  344.53     .06       0  385.51     .12       0
     445    .045       0   467.8     .12       0
Bank Sta=445,467.8
XS Rating Curve= 0 ,0
Exp/Cntr=0.3,0.1

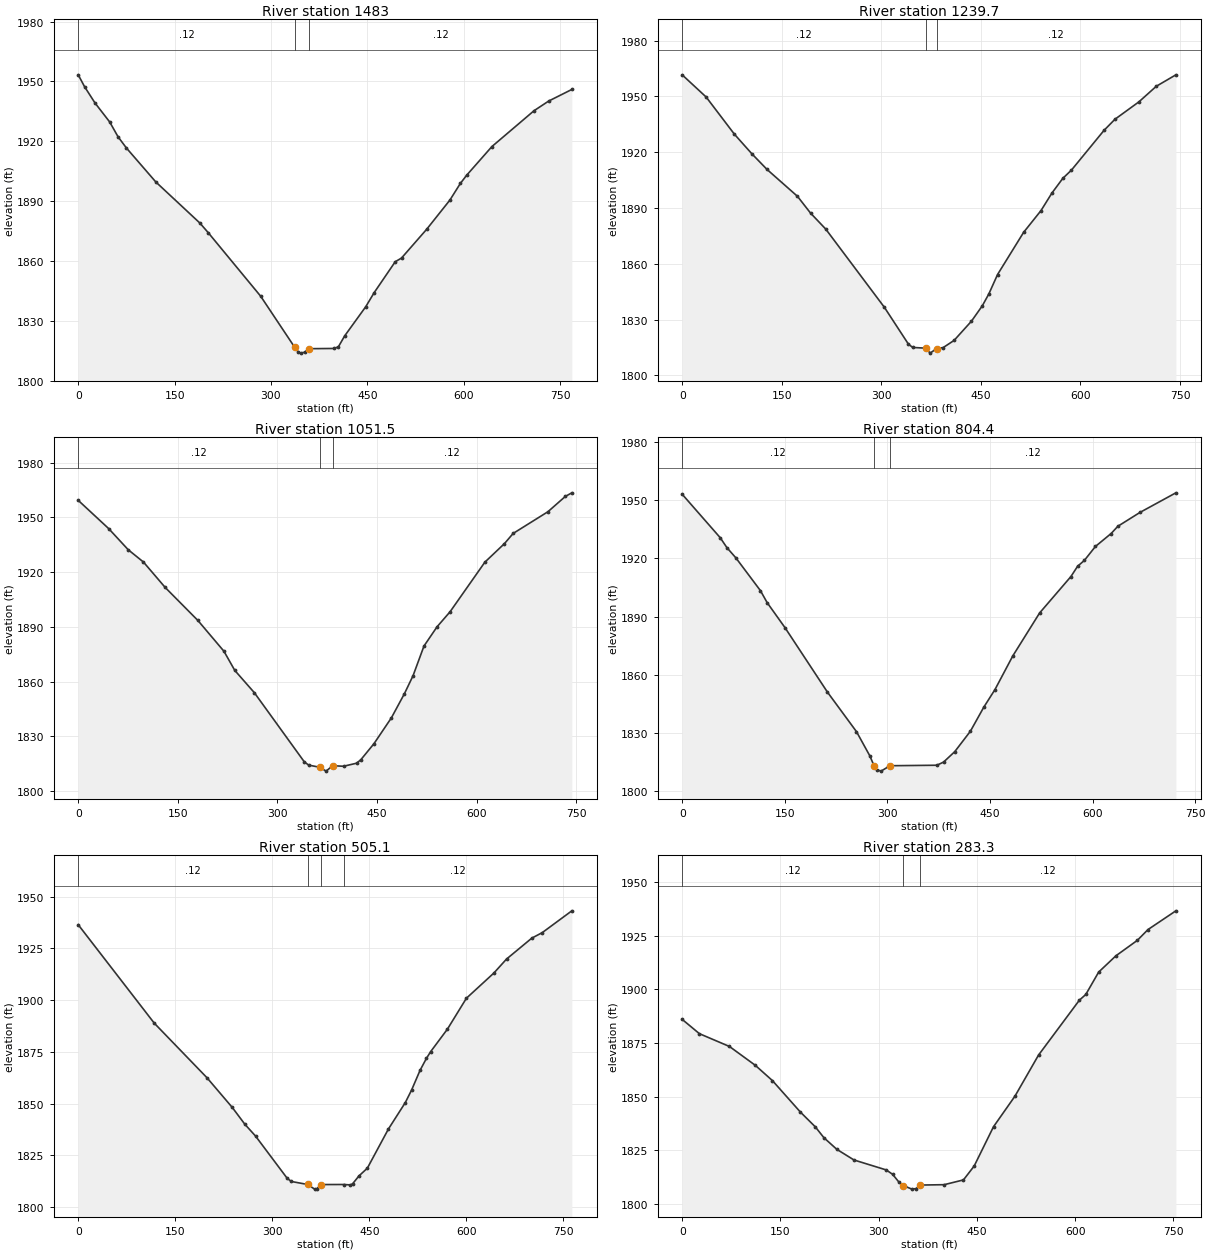
Type RM Length L Ch R = 1 ,1483    ,248.5,243.3,233.8
XS GIS Cut Line= 3
     2122582.481      250647.247     2122840.583      250469.568
     2123281.976       250359.22
#Sta/Elev= 30
       0  1953.3     9.8 1947.39    26.1  1939.2      49 1929.66      62 1922.24
    75.1 1916.59   120.8 1899.59   189.3 1879.02   202.4 1874.16     284 1842.32
   337.1 1816.64   342.8 1814.29   346.1  1813.8   352.6 1814.26   359.2 1816.02
   398.4 1816.14     405    1817   414.8 1822.48   447.6  1837.1   460.6 1844.11
   493.4 1859.61   503.2 1861.46   542.5 1875.94   578.5 1890.52   594.8 1898.87
   604.7 1903.01   643.9 1917.35   709.4  1935.3   732.3 1940.16   768.3 1945.97
#Mann= 3 ,-1 , 0
       0     .12       0   337.1    .045       0   359.2     .12       0
Bank Sta=337.1,359.2
XS Rating Curve= 0 ,0
Exp/Cntr=0.3,0.1

Type RM Length L Ch R = 1 ,1239.7  ,197.9,188.2,174.6
XS GIS Cut Line= 2
     2122687.332      250809.168     2123350.692      250472.809
#Sta/Elev= 30
       0  1961.6      36 1949.71    78.6 1929.71   104.8 1919.22   127.8 1910.75
   173.6 1896.32   193.3  1887.3   216.2  1878.7   304.7 1836.57   340.8 1816.83
   347.3 1815.05     367 1814.67   373.5    1812   383.4 1814.48   393.2 1814.99
   409.6 1818.84   435.8 1829.19   452.2  1837.5     462 1843.86   475.1 1854.27
   514.4 1876.97   540.6 1888.67     557 1898.07   573.4 1905.97   586.5 1910.44
   635.6 1931.82     652 1937.76   688.1 1947.12   714.3  1955.5   743.8 1961.65
#Mann= 3 ,-1 , 0
       0     .12       0     367    .045       0   383.4     .12       0
Bank Sta=367,383.4
XS Rating Curve= 0 ,0
Exp/Cntr=0.3,0.1

Type RM Length L Ch R = 1 ,1051.5  ,245.2,247.1,202.1
XS GIS Cut Line= 2
     2122846.721       251034.43     2123391.276      250528.157
#Sta/Elev= 30
       0 1959.28    45.9 1943.79    75.3 1932.22    98.3 1925.46     131 1911.55
   180.2 1893.49   219.5 1876.59   235.8 1866.12   265.3 1853.89   340.6 1815.96
   347.2 1814.21   363.6 1813.05   373.4 1810.92   383.2 1813.89   399.6 1813.59
   419.3 1815.26   425.8 1817.22   445.5 1825.98   471.7 1840.12   491.3 1853.32
   504.4 1863.26   520.8 1879.47   540.5 1890.01   560.1 1898.24   612.5 1925.41
     642 1935.58   655.1 1941.15   707.5 1953.05   733.7 1961.43   743.5  1963.4
#Mann= 3 ,-1 , 0
       0     .12       0   363.6    .045       0   383.2     .12       0
Bank Sta=363.6,383.2
XS Rating Curve= 0 ,0
Exp/Cntr=0.3,0.1

Type RM Length L Ch R = 1 ,804.4   ,313.5,299.3,257.6
XS GIS Cut Line= 2
     2123044.447      251180.285     2123461.416       250590.97
#Sta/Elev= 30
       0 1952.88    55.5 1930.57    65.3 1925.45    78.4  1920.2   114.3 1903.34
   124.1 1897.18   150.3 1884.25   212.3 1851.12   254.8 1830.76   274.4 1818.25
   280.9 1812.86   284.2 1811.18   290.7 1810.45   303.8 1813.23   372.4 1813.48
   382.2 1815.12   398.5 1820.47   421.4 1830.99     441 1843.37   457.3 1852.41
   483.4 1869.74   522.6 1891.83   568.4 1910.58   578.2 1915.89     588 1918.86
   604.3 1926.08   627.2 1932.72     637 1936.44   669.6 1943.62   721.9 1953.66
#Mann= 3 ,-1 , 0
       0     .12       0   280.9    .045       0   303.8     .12       0
Bank Sta=280.9,303.8
XS Rating Curve= 0 ,0
Exp/Cntr=0.3,0.1

Type RM Length L Ch R = 1 ,505.1   ,234,221.8,207.7
XS GIS Cut Line= 3
     2123387.055       251362.54     2123445.214      251004.984
      2123522.14       250611.48
#Sta/Elev= 30
       0 1936.44   117.5 1888.88   199.1 1862.46   238.2  1848.1   257.8 1839.92
   274.1  1834.3   323.1 1813.85   329.6 1812.31   354.8 1810.86   365.5 1808.62
   368.8 1808.73   375.3 1810.83  410.311810.855   420.9 1810.66   424.2 1811.18
     434 1814.99     447 1818.74   479.6 1837.68   505.7 1850.45   515.5 1856.57
   528.5 1866.04   538.3 1871.79   544.8 1875.04   570.9    1886   600.2 1900.91
   642.6 1913.07   662.2 1919.84   701.3 1929.96   717.6 1932.65   763.2 1943.16
#Mann= 4 ,-1 , 0
       0     .12       0   354.8    .045       0   375.3     .06       0
  410.31     .12       0
Bank Sta=354.8,375.3
XS Rating Curve= 0 ,0
Exp/Cntr=0.3,0.1

Type RM Length L Ch R = 1 ,283.3   ,225.4,230.7,234.5
XS GIS Cut Line= 2
     2123725.238      251352.353     2123566.262      250615.452
#Sta/Elev= 30
       0 1886.01    26.2 1879.37    72.1  1873.4   111.4 1864.65   137.7 1857.48
   180.3 1842.84   203.2  1835.9   216.3 1830.85     236 1825.43   262.2 1820.46
   311.4 1815.82   321.2 1813.78     331 1810.08   337.6 1808.52   350.7 1806.86
   357.3 1807.13   363.8 1808.76   399.9 1808.93   429.4 1811.16   445.8 1817.65
   475.3 1835.97     508  1850.2   544.1 1869.41   606.4 1894.99   616.2 1897.65
   635.9 1908.11   662.1 1915.67   694.9  1922.9   711.2 1927.94   753.8 1936.68
#Mann= 3 ,-1 , 0
       0     .12       0   337.6    .045       0   363.8     .12       0
Bank Sta=337.6,363.8
XS Rating Curve= 0 ,0
Exp/Cntr=0.3,0.1

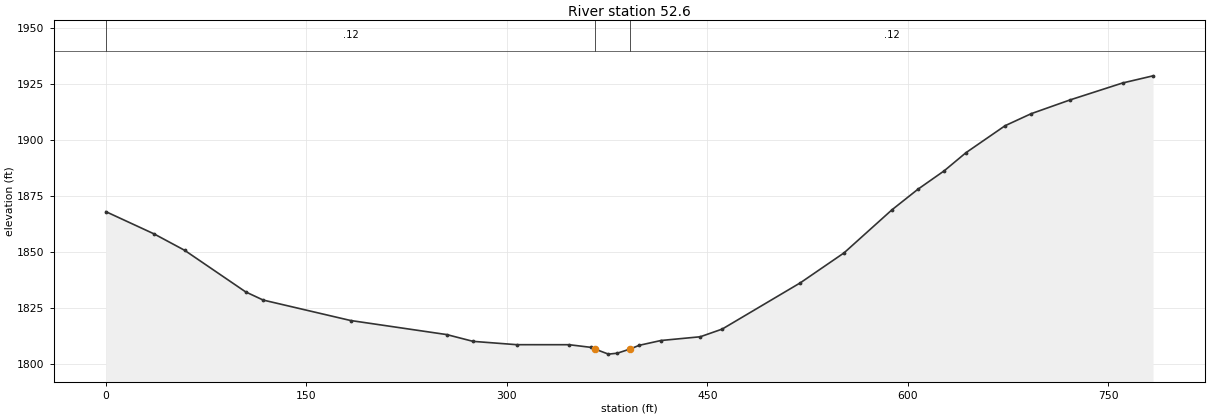
Type RM Length L Ch R = 1 ,52.6    ,55.3,52.6,49.2
XS GIS Cut Line= 3
      2123875.18       251293.43     2123844.938      250826.797
     2123641.074      250585.527
#Sta/Elev= 30
       0 1867.89      36 1857.96    58.9 1850.62   104.6 1832.01   117.7 1828.37
   183.1 1819.23   255.1 1812.93   274.7 1809.91   307.4 1808.42   346.6 1808.41
     363 1807.22   366.2 1806.41     376  1804.2   382.6 1804.61   392.4 1806.52
   398.9 1808.12   415.3 1810.29   444.7 1811.96   461.1 1815.39   519.7 1836.12
   552.3 1849.47   588.1  1868.7   607.6 1877.93   627.2 1886.14   643.5 1894.25
   672.8 1906.32   692.3 1911.69   721.6 1917.89   760.7 1925.42   783.5 1928.62
#Mann= 3 ,-1 , 0
       0     .12       0   366.2    .045       0   392.4     .12       0
Bank Sta=366.2,392.4
XS Rating Curve= 0 ,0
Exp/Cntr=0.3,0.1

Chan Stop Cuts=-1
Use User Specified Reach Order=0
Composite Channel Slope=5